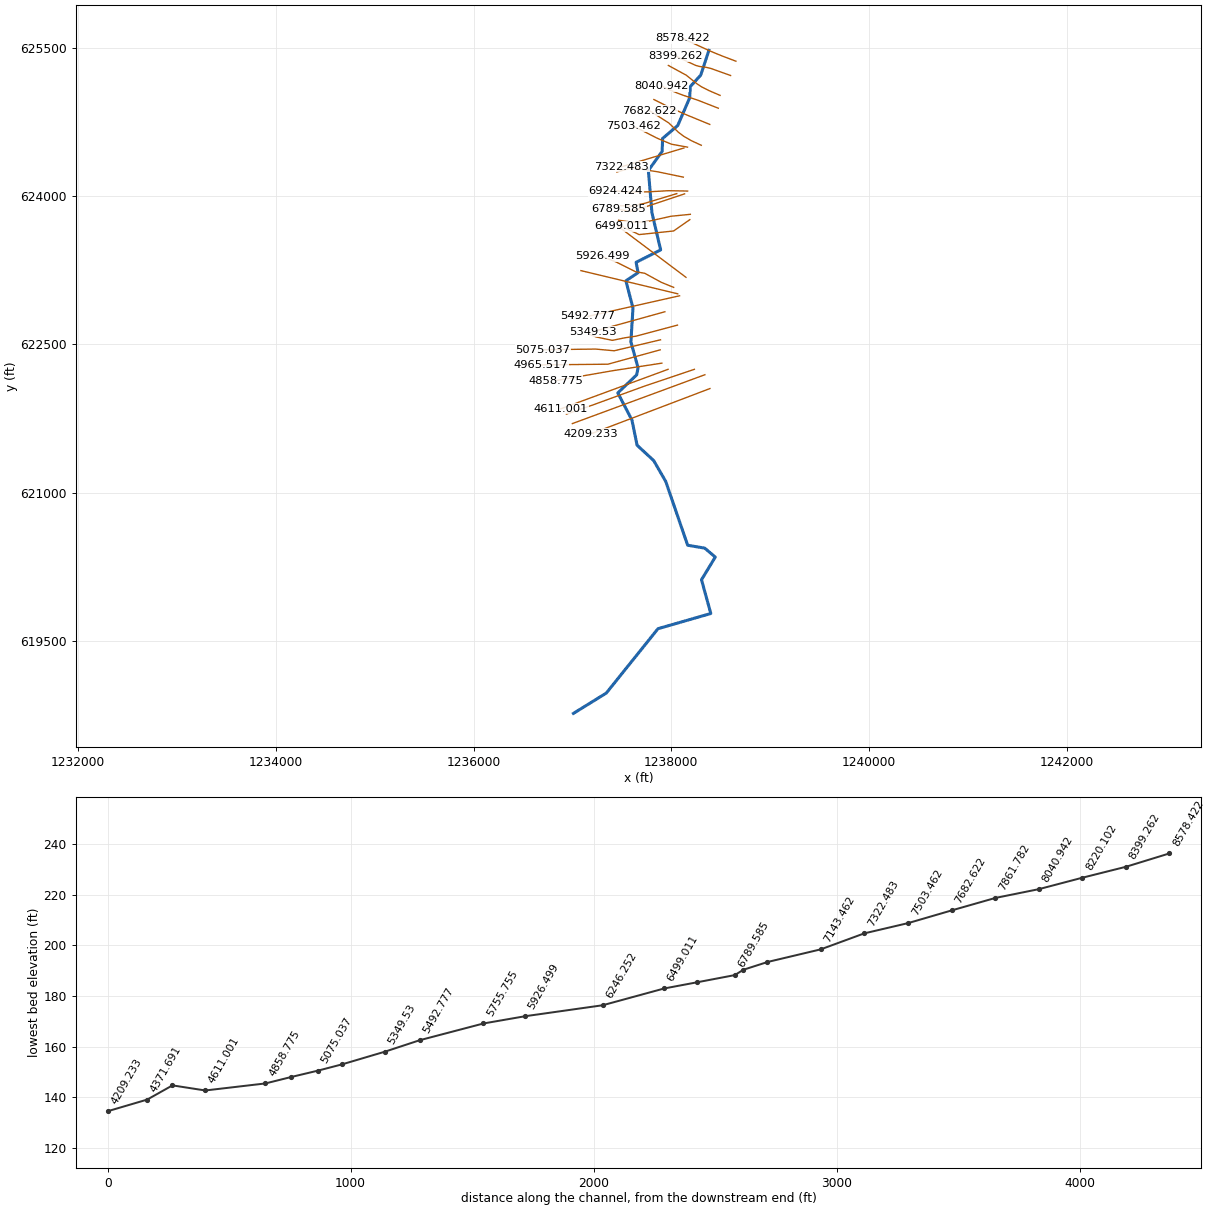
--- 340_ras.prj (project) ---

Proj Title=340
Current Plan=p01
Default Exp/Contr=0.3,0.1
English Units
Geom File=g01
Flow File=f01
Plan File=p01
Y Axis Title=Elevation
X Axis Title(PF)=Main Channel Distance
X Axis Title(XS)=Station
BEGIN DESCRIPTION:
RFD model 340 exported to HEC-RAS
END DESCRIPTION:

--- 340_ras.p01 (plan) ---

Plan Title=Plan 01
Program Version=4.10
Short Identifier=Plan 01
Geom File=g01
Flow File=f01
Subcritical Flow
Calc Critical at every XS
Secant Critical Depth

--- 340_ras.f01 (steady flow) ---

Flow Title=Flow 01
Program Version=5.01
Number of Profiles= 5
Profile Names=10yr,25yr,50yr,100yr,500yr
River Rch & RM=340,27,8578.422
  517.89  645.45  777.17   866.5 1075.49
River Rch & RM=340,27,8399.262
  522.89  652.58  786.01   877.6 1091.25
River Rch & RM=340,27,8220.102
  532.65  666.57  803.36  899.43 1122.33
River Rch & RM=340,27,8040.942
  540.59  677.97  817.49  917.26 1147.79
River Rch & RM=340,27,7861.782
  541.63  679.47  819.35  919.61 1151.16
River Rch & RM=340,27,7682.622
  551.91  694.27  837.73  942.85 1184.46
River Rch & RM=340,27,7503.462
  559.93  705.84   852.1  961.07 1210.67
River Rch & RM=340,27,7322.483
   562.9  710.13  857.42  967.83 1220.39
River Rch & RM=340,27,7143.462
  620.28   793.7  961.42 1100.92 1414.02
River Rch & RM=340,27,6924.424
  625.75  801.73  971.43 1113.82 1432.98
River Rch & RM=340,27,6825.255
  628.25   805.4  976.01 1119.74 1441.68
River Rch & RM=340,27,6632.513
  631.56  810.27  982.07 1127.57 1453.22
River Rch & RM=340,27,6499.011
  634.44   814.5  987.35 1134.39 1463.27
River Rch & RM=340,27,6246.252
  674.99  874.45  1062.2 1231.63 1607.48
River Rch & RM=340,27,5926.499
  677.22  877.76 1066.34 1237.02 1615.53
River Rch & RM=340,27,5755.755
  680.54  882.69  1072.5 1245.08 1627.56
River Rch & RM=340,27,5492.777
  692.15  899.97 1094.11 1273.35 1669.87
Boundary for River Rch & Prof#=340,27,1
Up Type= 0
Dn Type= 2
Boundary for River Rch & Prof#=340,27,2
Up Type= 0
Dn Type= 2
Boundary for River Rch & Prof#=340,27,2
Up Type= 0
Dn Type= 2
Boundary for River Rch & Prof#=340,27,2
Up Type= 0
Dn Type= 2
Boundary for River Rch & Prof#=340,27,2
Up Type= 0
Dn Type= 2

--- 340_ras.g01 (geometry) ---

Geom Title=340
Program Version=4.10

River Reach=340,27
Reach XY= 30
1238381.38743781625472.4193262481238298.05412176625221.586069834
 1238193.0541494625106.5861070211238186.38748135624991.586141336
1238065.55417551 624711.586227981237913.05421673624581.586271002
 1237908.0542144624450.7529766711237768.88758316624257.419704782
1237804.72089351623830.7531637091237893.05418981623454.086606324
 1237644.7209261623328.2533175621237664.72091716623224.086681246
1237541.38761781623141.586709324 1237613.0542553622865.753455784
1237592.04955455622523.3951416221237664.54952555622261.728550507
1237650.38286098622190.0619055651237459.54957864622007.561965256
1237602.88286166621732.5620427311237654.54950569621478.395450054
1237822.88278482621322.5621580861237944.54940945 621111.72888381
1238166.21599193620466.7290688431238338.71594018620437.562405822
1238445.38257273620346.7290963621238306.21594045620117.562501769
1238400.38256939619775.8959338231237866.21605588619622.562661543
1237342.88285802618970.8962035731237011.12904073618765.888549558

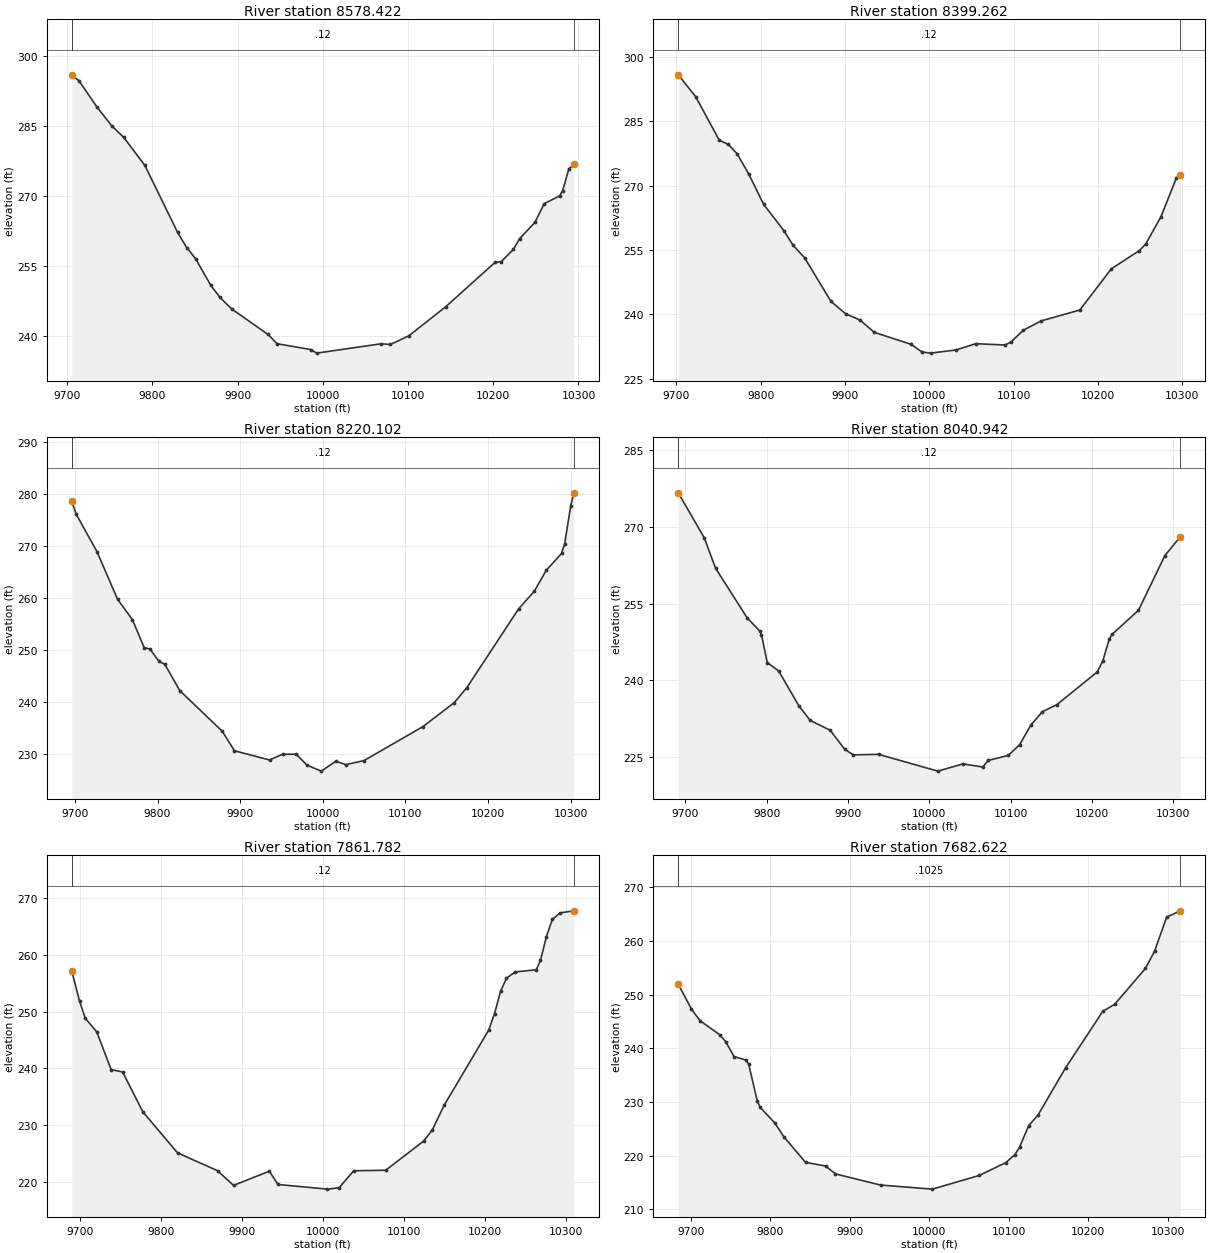
Type RM Length L Ch R = 1 ,8578.422,179.160000,179.160000,179.160000
XS GIS Cut Line= 6
1238654.66613954 625362.693004231238524.01452277625412.092618281
1238422.74757228625453.2604350251238381.89345638625471.098741073
1238380.06685264625471.9133076751238113.12882756625594.106728093
#Sta/Elev= 30
9705.427296.01099713.907294.73419734.952  289.11 9752.49285.0331 9766.52282.5613
9791.073276.60569829.655262.17759840.178258.94929850.755256.54619868.463250.8611
9879.087248.29429893.254245.74019935.752 240.2899946.377238.29949985.669237.0548
9992.829236.282110068.54238.291910079.37238.137810101.02240.010210144.32 246.253
10202.05255.746410209.27255.8961 10223.7258.565210230.92260.847210248.96264.3559
10259.78268.358310277.82270.023410281.43 271.12210288.65275.776110294.58276.8565
#Mann= 3 , 0 , 0
9705.427    0.12       09705.427    0.12       010294.58    0.12       0
#XS Ineff= 2 , 0
       0                               0
Bank Sta=9705.427,10294.58
Exp/Cntr=0.3,0.1

Type RM Length L Ch R = 1 ,8399.262,179.160000,179.160000,179.160000
XS GIS Cut Line= 6
1238600.51865989625218.168058021 1238402.1050207625289.114135684
1238351.08336918625301.301853074 1238285.7164736 625309.69079499
 1238245.9137061625320.7560025041238042.16353608625415.812737167
#Sta/Elev= 30
9702.319295.81399723.019290.71999751.024280.56419761.717 279.6069772.028 277.446
 9786.03272.67099803.533265.67219827.569259.52489838.491256.10739852.324  253.16
9883.449243.03159900.741240.17839917.911238.69199934.776235.83769978.368 233.055
9991.594 231.257 10001.5230.997810031.43231.728110055.13233.193410089.92232.8934
10097.03233.603910111.26 236.305 10132.6 238.50410178.47241.035110215.88250.6352
 10249.2254.8996 10256.5256.369310274.75  262.79   10293271.795810297.65272.4683
#Mann= 3 , 0 , 0
9702.319    0.12       09702.319    0.12       010297.65    0.12       0
#XS Ineff= 2 , 0
       0                               0
Bank Sta=9702.319,10297.65
Exp/Cntr=0.3,0.1

Type RM Length L Ch R = 1 ,8220.102,179.160000,179.160000,179.160000
XS GIS Cut Line= 6
1238494.29043568625017.2110352881238381.27572776625065.852215657
1238306.02087797 625103.951017471238260.20348958625134.251582832
1238152.95907881625220.717209939 1237970.8309965625319.965262531
#Sta/Elev= 30
9696.171278.58069701.653276.10429726.656268.92199751.659259.74689769.518255.8573
9783.805250.45399790.949250.17929801.664247.80459808.808247.24919826.887242.1872
9878.369 234.3569893.079 230.6089935.616228.8344 9951.35229.93349967.945229.9438
9980.927227.83599998.238226.689310015.71228.586910028.06227.940310049.91228.7217
10121.13235.245510159.22239.892810174.33 242.75210237.22257.9617 10256.2261.3428
10270.52265.343610289.01268.577810292.71270.411710300.11277.751410303.87280.2422
#Mann= 3 , 0 , 0
9696.171    0.12       09696.171    0.12       010303.87    0.12       0
#XS Ineff= 2 , 0
       0                               0
Bank Sta=9696.171,10303.87
Exp/Cntr=0.3,0.1

Type RM Length L Ch R = 1 ,8040.942,179.160100,179.160100,179.160100
XS GIS Cut Line= 6
1238476.35905437624887.1697749611238277.23125015624965.338059655
1238120.18961092625018.7574506621238067.66086367625038.096083286
1237992.76925173625069.2307988011237901.09596277625111.529479302
#Sta/Elev= 30
9691.072276.67689723.038267.87749737.136261.87349775.906252.18349791.655249.5653
9793.529248.91489800.578243.44479814.677241.78519839.349235.00919853.447232.1012
9878.119 230.1699895.742226.48979906.295225.35729937.522225.462810010.46222.1716
10041.47223.585410065.72222.981410072.66224.279110097.14225.238110111.12227.3323
10125.11231.222310139.29233.822810157.06235.1883 10206.8241.615510213.53243.7443
10221.36247.962610224.84248.945210257.36253.654910289.88264.363710308.93 268.095
#Mann= 3 , 0 , 0
9691.072    0.12       09691.072    0.12       010308.93    0.12       0
#XS Ineff= 2 , 0
       0                               0
Bank Sta=9691.072,10308.93
Exp/Cntr=0.3,0.1

Type RM Length L Ch R = 1 ,7861.782,179.160000,179.160000,179.160000
XS GIS Cut Line= 6
1238389.82387307624723.3981803631238127.66464292624831.187704149
1238104.90128677624841.9093983181238103.10658686624842.792037683
1237963.23452531624905.5192317941237824.43367426624975.187348393
#Sta/Elev= 30
9690.384257.17359700.049251.82289707.034248.83399721.223246.4221 9738.96239.7672
9753.149239.3529 9777.98232.34039820.836225.08829870.211221.93849889.857219.3446
9934.063 221.8629944.705219.512610005.68218.693410020.06 218.93210038.04221.9303
10077.59222.024410124.34227.169610135.13229.153510149.51233.449310204.47246.7123
10211.81249.654710219.15253.5516 10226.5255.893710237.51257.003610263.21257.3746
10268.46259.034710275.77263.230610283.08266.259710292.57267.4082 10309.6267.7743
#Mann= 3 , 0 , 0
9690.384    0.12       09690.384    0.12       0 10309.6    0.12       0
#XS Ineff= 2 , 0
       0                               0
Bank Sta=9690.384,10309.6
Exp/Cntr=0.3,0.1

Type RM Length L Ch R = 1 ,7682.622,179.160000,179.160000,179.160000
XS GIS Cut Line= 6
1238304.13040241624512.4417027751238202.40485045 624559.60655879
1238125.87213464624603.7951558231238073.27727995624643.568098264
1237975.00732842624738.4394420911237782.28468436624861.369034839
#Sta/Elev= 30
9683.892251.97859700.322247.36579711.454245.13499736.241242.5329 9743.69241.2342
9754.216238.4662 9768.85237.84169772.509237.10139783.484230.15069787.143229.0095
9805.644 226.0819816.863223.54119844.195218.77729869.332218.09629881.798216.6293
9938.593214.5518 10003.9213.792410062.83216.335910096.34218.729210107.83220.2244
10113.63221.600410125.21225.6377 10136.8227.566910171.55236.370810218.58246.9143
 10233.5248.211710272.13254.8925 10283.6258.0888 10298.9264.453110316.05265.6103
#Mann= 3 , 0 , 0
9683.892  0.1025       09683.892  0.1025       010316.05  0.1025       0
#XS Ineff= 2 , 0
       0                               0
Bank Sta=9683.892,10316.05
Exp/Cntr=0.3,0.1

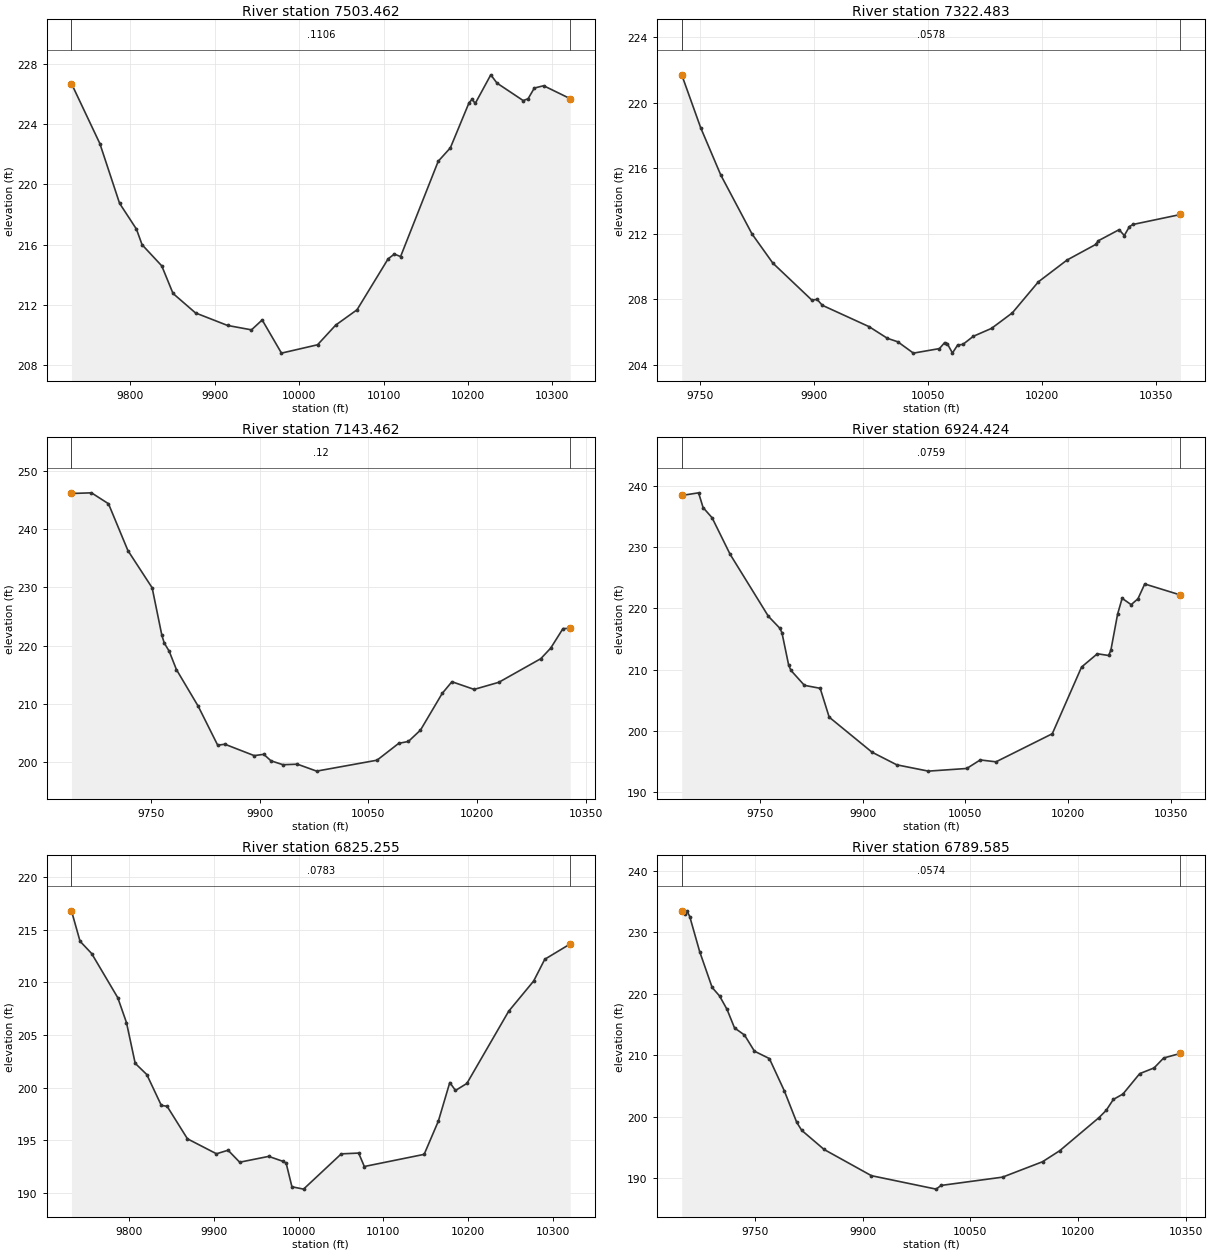
Type RM Length L Ch R = 1 ,7503.462,180.978700,180.978700,180.978700
XS GIS Cut Line= 6
1238164.74840197624493.584755898 1238002.5239062  624523.1283997
1237906.48794988624563.1024018381237904.63991627624563.867105469
1237852.69018042624586.330162674 1237618.0484663624706.548472494
#Sta/Elev= 30
9730.084 226.7049763.733222.71299787.077218.74459807.086217.02599813.755215.9895
9837.099214.58249850.438212.74939877.116211.45339915.035210.62159943.464210.3281
9956.129210.98659979.001208.780610021.76209.335710043.21210.641910068.56211.6627
10105.43215.0519 10112.8215.366310120.17215.2016 10164.8221.539610179.16222.4281
10201.27225.424310204.96225.662510208.65225.381510227.08227.285710234.45226.7353
10265.53225.573310271.32225.695910278.69226.406210289.75  226.5610321.24225.7004
#Mann= 3 , 0 , 0
9730.084  0.1106       09730.084  0.1106       010321.24  0.1106       0
#XS Ineff= 2 , 0
       0                               0
Bank Sta=9730.084,10321.24
Exp/Cntr=0.3,0.1

Type RM Length L Ch R = 1 ,7322.483,179.021300,179.021300,179.021300
XS GIS Cut Line= 2
1238128.29006863624484.9042003451237499.81784639624295.668089241
#Sta/Elev= 30
9725.484221.69619750.366218.47339776.803215.58639817.919 211.989 9845.33210.2078
9896.725 207.9479903.577207.9922 9910.43207.63239972.104206.32499996.088205.6163
10009.79205.403210030.35204.711110064.61204.988110071.47205.352310074.89 205.292
10081.75204.7181 10088.6205.206910095.45205.241910109.16205.737110133.14 206.221
10160.55207.167910194.82209.062110232.51210.3915 10270.2211.341810273.62211.5672
10301.03 212.24410307.88211.889810314.74212.437110319.33212.563510381.83213.1721
#Mann= 3 , 0 , 0
9725.484  0.0578       09725.484  0.0578       010381.83  0.0578       0
#XS Ineff= 2 , 0
       0                               0
Bank Sta=9725.484,10381.83
Exp/Cntr=0.3,0.1

Type RM Length L Ch R = 1 ,7143.462,219.037200,219.037200,219.037200
XS GIS Cut Line= 6
1238122.62332296624190.0861275491237864.73263472624243.750589192
1237775.71942738624257.5252633091237768.47432548 624259.31674917
1237611.72281852624287.5923918341237449.47062421624241.848644778
#Sta/Elev= 30
9640.039246.15789667.688246.27179691.146244.39539717.955236.34759751.466229.9367
 9764.87221.76519768.221220.42679774.924 219.0519784.977215.87519815.137209.5502
9841.946202.87579851.999203.02949892.458201.07149905.597201.29689915.557200.1831
9932.156199.50859952.075199.60049978.634198.406410062.03200.286610092.03203.1862
10105.37203.510110122.04205.459910152.04211.769710165.49213.782210196.17212.4628
10230.26213.6847 10288.2 217.74510301.84219.553210318.88 222.92210328.86 222.971
#Mann= 3 , 0 , 0
9640.039    0.12       09640.039    0.12       010328.86    0.12       0
#XS Ineff= 2 , 0
       0                               0
Bank Sta=9640.039,10328.86
Exp/Cntr=0.3,0.1

Type RM Length L Ch R = 1 ,6924.424,99.169900,99.169900,99.169900
XS GIS Cut Line= 6
1238166.01289536624049.328488118 1237972.6022589624052.989751439
1237776.82899256624041.9022734351237629.53969056624038.749915637
1237534.98353493 624041.858234291237439.99923234624050.596999061
#Sta/Elev= 30
 9636.52238.44979661.066238.87949667.633236.47339680.767234.80399707.035228.8376
9762.826 218.708 9779.23216.79199782.511216.05859792.353210.74119795.634209.8766
9815.319207.42839838.292206.94599851.427202.23399913.817196.51249949.937194.4441
9996.006193.414510051.91193.8471 10071.6195.241810094.57194.934210176.62199.5231
10219.29210.420710242.27212.587810258.68212.307910261.96213.140710271.82219.0686
10278.41221.647710291.59220.610110301.48221.569210311.36223.990210363.46222.1857
#Mann= 3 , 0 , 0
 9636.52  0.0759       0 9636.52  0.0759       010363.46  0.0759       0
#XS Ineff= 2 , 0
       0                               0
Bank Sta=9636.52,10363.46
Exp/Cntr=0.3,0.1

Type RM Length L Ch R = 1 ,6825.255,35.669900,35.669900,35.669900
XS GIS Cut Line= 4
1238056.02444366624023.3156586741237734.84388807623926.093436465
1237604.63555476623896.5795475541237484.84388807623901.787880912
#Sta/Elev= 30
9731.697 216.7749741.814213.88749755.525212.72019786.376208.52519796.659206.1624
9806.943202.29759820.654201.23019837.793 198.3049844.649198.21739868.644 195.132
9902.922193.71019916.634194.04649930.345192.90939964.624193.46249981.763192.9841
9985.191192.82529992.047190.577710005.76190.354110050.32193.702410070.82193.7767
10077.55192.502110148.19193.655110165.01196.818810178.47200.4744 10185.2199.7205
10198.65200.387310247.96207.235910277.52210.110310290.65212.175110320.69213.6315
#Mann= 3 , 0 , 0
9731.697  0.0783       09731.697  0.0783       010320.69  0.0783       0
#XS Ineff= 2 , 0
       0                               0
Bank Sta=9731.697,10320.69
Exp/Cntr=0.3,0.1

Type RM Length L Ch R = 1 ,6789.585,157.071800,157.071800,157.071800
XS GIS Cut Line= 4
1238135.62031555624021.1310521961237724.62494516623884.132595405
1237587.62648839623844.2599102111237472.09793898623863.685064539
#Sta/Elev= 30
9648.805233.46879652.997232.99829656.456233.36799659.914232.54099673.747226.8305
9691.039221.01829701.414219.62329711.788217.43849722.163214.43519735.997213.2852
 9749.83210.6585 9770.58209.45849791.329204.22079808.621199.08549815.537 197.792
9846.662194.6821 9912.37190.424810002.29188.2392 10009.2188.839710094.61190.1876
10150.17192.689610174.09194.485710228.65199.863110238.63201.042110248.61202.8188
10261.92 203.69510285.21207.008810305.17207.935210318.48209.549310341.87210.3025
#Mann= 3 , 0 , 0
9648.805  0.0574       09648.805  0.0574       010341.87  0.0574       0
#XS Ineff= 2 , 0
       0                               0
Bank Sta=9648.805,10341.87
Exp/Cntr=0.3,0.1

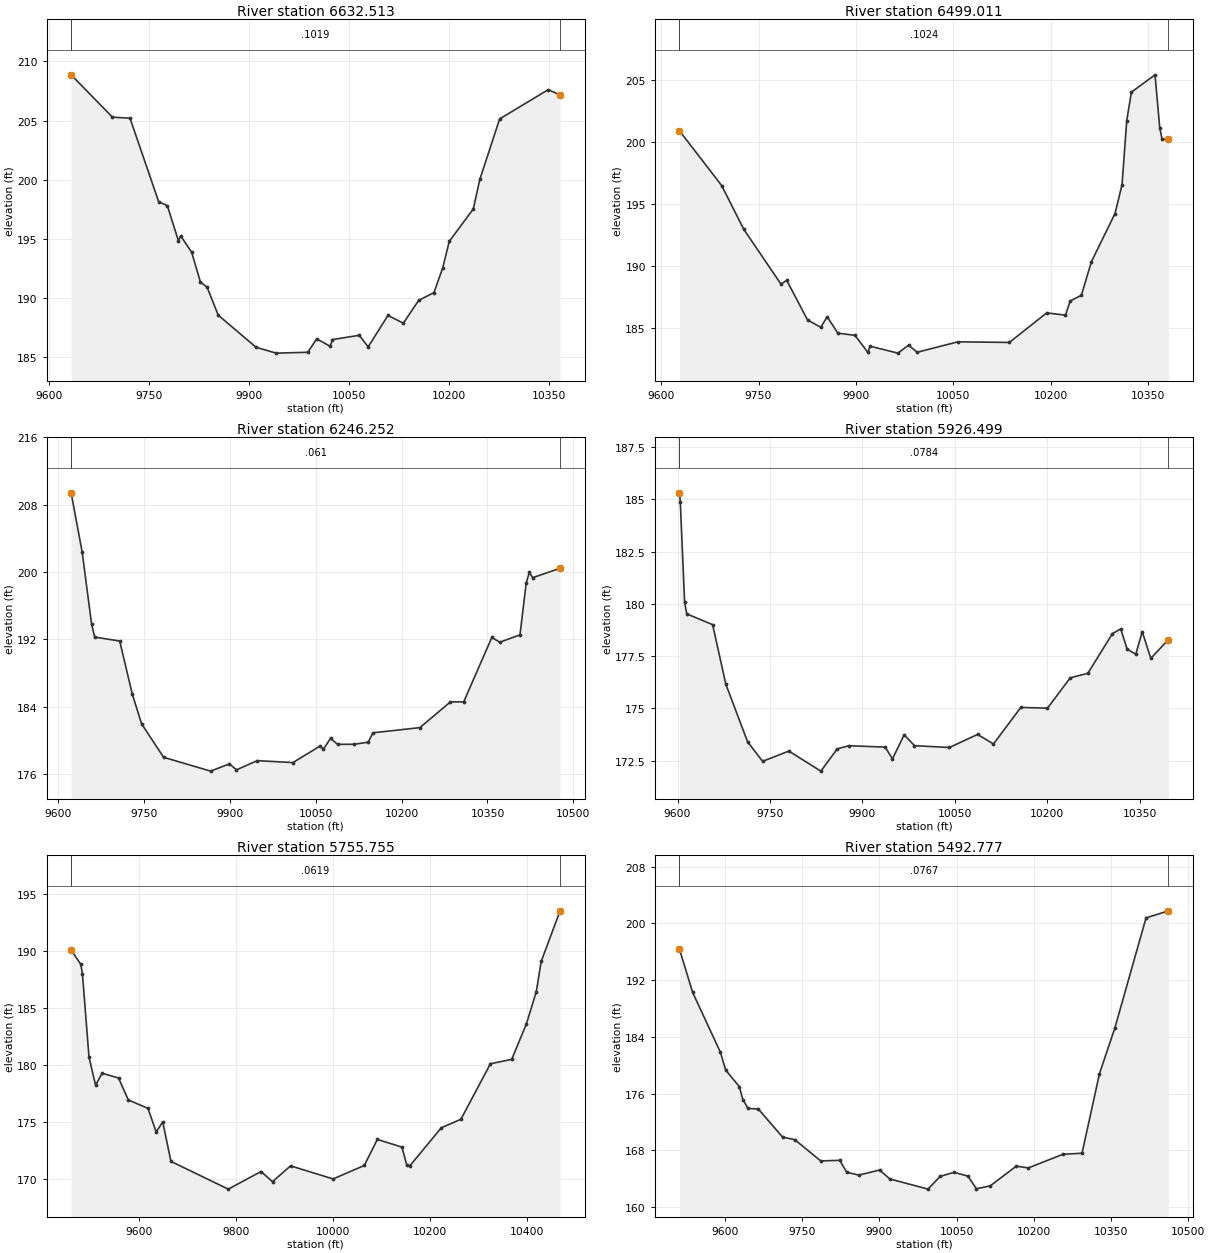
Type RM Length L Ch R = 1 ,6632.513,133.502100,133.502100,133.502100
XS GIS Cut Line= 6
1238193.62482566623813.9839218871237997.67984792 623794.40354984
1237787.21841927623747.2777643281237706.12596445623735.794733131
1237588.26195932623736.9572289121237467.76804244623753.985911135
#Sta/Elev= 30
9632.787208.86569694.917 205.2919721.226205.20559764.187198.16999777.419 197.805
 9793.96194.84839797.268195.26929813.808  193.899827.041191.36419837.036190.9402
9853.738188.57259910.528185.86479940.691185.36759988.126 185.43810001.69186.5661
10021.97185.948310025.35 186.511 10065.6186.874110078.92185.8959 10108.7188.5503
10131.78187.896910154.76189.819310177.74190.478210190.87192.553110200.73194.8024
10236.86197.542210246.73200.048410276.44205.143510349.43207.6119 10367.2207.1647
#Mann= 3 , 0 , 0
9632.787  0.1019       09632.787  0.1019       0 10367.2  0.1019       0
#XS Ineff= 2 , 0
       0                               0
Bank Sta=9632.787,10367.2
Exp/Cntr=0.3,0.1

Type RM Length L Ch R = 1 ,6499.011,252.759100,252.759100,252.759100
XS GIS Cut Line= 4
  1238188.185902623760.0778114651238024.12340197623645.494478136
1237675.16506863623609.0361447931237492.87340197623694.973644793
#Sta/Elev= 30
9628.387200.89859693.352196.47859727.279192.95319784.577188.52969793.397188.8377
9825.411185.64419845.746185.04579855.642 185.8959872.136184.57529898.525184.3936
9918.318183.01979921.616183.52119964.499 182.9619980.993183.59889994.187183.0313
10056.86 183.87410136.03183.822710193.38186.2044 10222.4186.026810229.65187.1722
 10246.9187.626110262.29190.336810298.57194.213910309.45196.5457 10316.7201.7235
10323.84204.016110360.23205.415910367.48201.149510371.11200.206310380.89200.2405
#Mann= 3 , 0 , 0
9628.387  0.1024       09628.387  0.1024       010380.89  0.1024       0
#XS Ineff= 2 , 0
       0                               0
Bank Sta=9628.387,10380.89
Exp/Cntr=0.3,0.1

Type RM Length L Ch R = 1 ,6246.252,319.752400,319.752400,319.752400
XS GIS Cut Line= 2
1238149.12340197623176.7444781361237466.83173531623689.765311465
#Sta/Elev= 30
9623.125209.40299642.458202.35819658.835193.82229664.295192.26199707.968191.7998
9729.805185.52039746.182181.95919784.558177.98819866.654176.34219899.493177.2003
9911.807176.49599948.172177.587410010.32177.358410057.36179.303910063.68178.9568
   10076180.229210088.31179.529210117.05179.531410141.68  179.7810150.16 180.896
10231.98181.509410285.34184.566310308.48184.568410357.61192.220210371.55191.6558
10406.74192.527110417.66198.704810423.12199.954910429.01199.324410476.77200.4375
#Mann= 3 , 0 , 0
9623.125   0.061       09623.125   0.061       010476.77   0.061       0
#XS Ineff= 2 , 0
       0                               0
Bank Sta=9623.125,10476.77
Exp/Cntr=0.3,0.1

Type RM Length L Ch R = 1 ,5926.499,170.743900,170.743900,170.743900
XS GIS Cut Line= 6
1238024.62742235623074.9793561311237900.31716335623125.743368602
1237731.87028003623217.6436465971237637.91535302623233.879534063
1237444.28986841623331.3192136841237300.97091523623387.334006947
#Sta/Elev= 30
9603.191185.30819604.524184.86119611.516180.06959615.012179.52079656.962179.0064
9678.405176.15969713.682173.40729738.138172.47229780.704172.96259832.621172.0035
 9859.16173.06679878.117173.21889937.007173.15189948.889172.58979967.924173.7438
9984.499173.221510041.32173.133610086.99173.758610112.82173.3012 10157.1175.0485
10200.45175.013910237.38176.463410265.96176.679710305.83178.577710319.32178.8036
 10329.8177.827510343.76177.594610354.23178.668110368.19177.394610396.78178.2955
#Mann= 3 , 0 , 0
9603.191  0.0784       09603.191  0.0784       010396.78  0.0784       0
#XS Ineff= 2 , 0
       09819.832        10127.29       0
Bank Sta=9603.191,10396.78
Exp/Cntr=0.3,0.1

Type RM Length L Ch R = 1 ,5755.755,262.978400,262.978400,262.978400
XS GIS Cut Line= 2
1238065.79006863 623010.077811451237086.62340197 623244.45281145
#Sta/Elev= 30
9460.961190.06049480.959188.81189484.332187.96279497.826180.6776 9511.32178.2515
9524.814179.2882 9558.55178.87259578.791176.94939619.273176.2122 9636.14174.1469
9649.634175.02819666.502171.57579784.575169.14849852.045170.6898 9875.66169.7976
9912.768171.185410000.48170.040710064.58171.216210091.56173.496510142.17172.8247
10152.29171.223110159.03171.214410223.13174.511510263.61175.261410324.34 180.116
10368.19180.499910398.55183.616510418.79186.421610428.92189.069710467.79193.4957
#Mann= 3 , 0 , 0
9460.961  0.0619       09460.961  0.0619       010467.79  0.0619       0
#XS Ineff= 2 , 0
       09762.582        10067.63       0
Bank Sta=9460.961,10467.79
Exp/Cntr=0.3,0.1

Type RM Length L Ch R = 1 ,5492.777,143.246800,143.246800,143.246800
XS GIS Cut Line= 2
1238084.46948844 622990.016959281237157.38615513622781.683625951
#Sta/Elev= 30
9511.399  196.359537.027190.2456 9590.83181.83699600.918179.34169627.819176.9539
9634.544175.14699644.632173.90869664.808 173.8059711.885169.84999735.424169.4986
9785.863166.50079822.853166.58399836.303164.90679859.842164.50359900.194165.2165
 9920.37163.95849994.348162.525310017.89164.316710044.79164.892610071.69 164.367
 10088.5162.5745 10115.4162.991410165.84165.764310189.38165.514710256.63 167.439
10293.62167.582610327.59178.806410357.51185.261110418.04 200.756 10461.6201.7561
#Mann= 3 , 0 , 0
9511.399  0.0767       09511.399  0.0767       0 10461.6  0.0767       0
#XS Ineff= 2 , 0
       0                               0
Bank Sta=9511.399,10461.6
Exp/Cntr=0.3,0.1

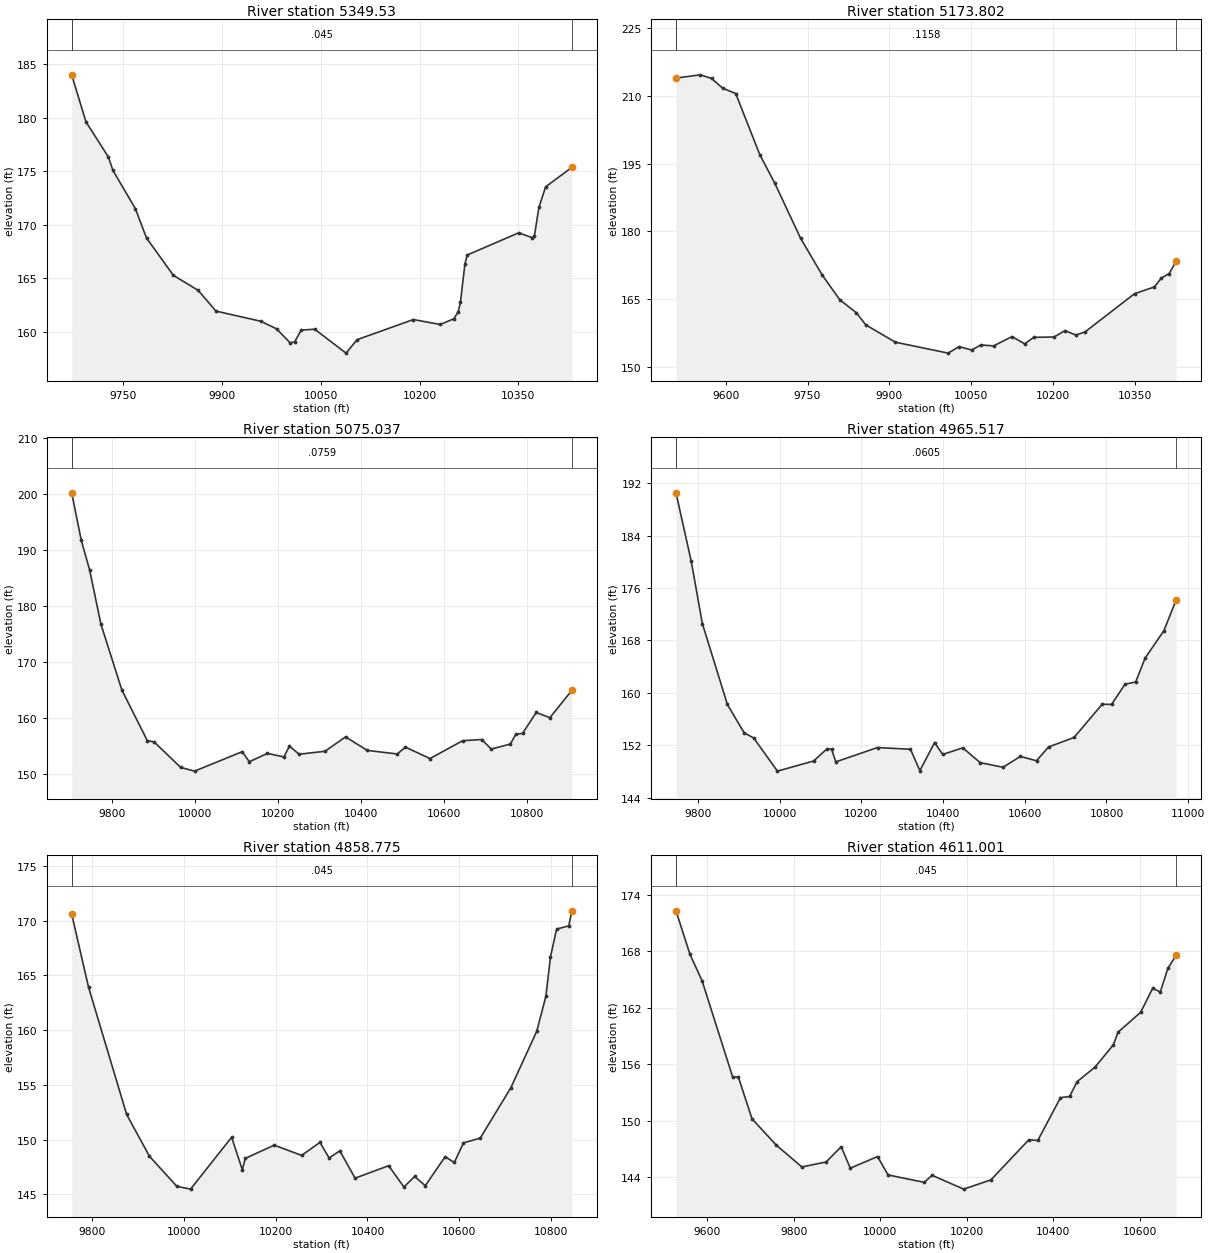
Type RM Length L Ch R = 1 , 5349.53,175.727600,175.727600,175.727600
XS GIS Cut Line= 2
1237936.03198847622828.5586259511237204.26115513622625.433625951
#Sta/Elev= 30
9671.729184.01419693.444179.61839727.492176.33179734.302175.08569768.351171.5161
9785.375168.76099826.234165.26529863.688163.87189890.927161.92469959.024160.9753
9982.859160.268510003.29158.9704 10010.1159.034610020.31160.144610040.74160.2326
10088.41157.997110105.12159.253910190.56161.135610231.42160.675210251.84161.2022
10258.65161.843210262.06162.754710268.87166.325410272.27167.167910350.59 169.246
10371.02168.790110374.42168.975710381.23171.622610391.44173.544610431.17175.3571
#Mann= 3 , 0 , 0
9671.729   0.045       09671.729   0.045       010431.17   0.045       0
#XS Ineff= 2 , 0
       0                10335.65       0
Bank Sta=9671.729,10431.17
Exp/Cntr=0.3,0.1

Type RM Length L Ch R = 1 ,5173.802,98.765500,98.765500,98.765500
XS GIS Cut Line= 6
1238063.46751857622693.3820565041237642.32198837622581.104339257
1237533.62026137622565.3645098951237403.96785158622539.164164528
1237239.85143292622573.350292623 1237174.7472662622599.391959295
#Sta/Elev= 30
9509.207213.98429554.069214.7003 9574.43213.88749594.791 211.7279618.546210.5601
9662.661196.99719689.821190.74119737.478178.4375 9776.56170.39759808.963164.8645
  9839.6161.9447 9856.62159.28579910.853155.434710007.64153.010410027.51154.4566
 10050.7153.705610067.39154.827310090.82154.611810124.29156.667210147.72155.0802
10164.45156.511710201.29156.5824 10221.4157.994410241.51157.010410258.26157.7145
10348.75166.183910385.37167.696410397.88 169.65310412.02170.610710424.96173.3788
#Mann= 3 , 0 , 0
9509.207  0.1158       09509.207  0.1158       010424.96  0.1158       0
#XS Ineff= 2 , 0
       0                 10284.4       0
Bank Sta=9509.207,10424.96
Exp/Cntr=0.3,0.1

Type RM Length L Ch R = 1 ,5075.037,109.519900,109.519900,109.519900
XS GIS Cut Line= 4
 1237891.7611551622544.704459295 1237423.0111551622433.593348175
1237235.51115513622450.9544592951236700.78893289622444.010014832
#Sta/Elev= 30
9703.412200.17979726.622191.68719746.853186.36839773.827176.76169824.403164.9933
9885.665155.97249901.953155.75629966.016151.20389999.461150.540910114.37154.0106
10131.23152.212410175.06153.705410214.83153.069110228.01155.016110251.08153.5538
10313.68154.0829 10363.1156.649410415.64154.234710487.83153.601310507.51154.8266
10566.57152.779710645.32155.970310691.26156.177410714.22154.472410760.16 155.369
10773.28157.102210789.69157.2806 10822.5161.001210855.31160.067310908.22164.9297
#Mann= 3 , 0 , 0
9703.412  0.0759       09703.412  0.0759       010908.22  0.0759       0
#XS Ineff= 2 , 0
       0                10281.24       0
Bank Sta=9703.412,10908.22
Exp/Cntr=0.3,0.1

Type RM Length L Ch R = 1 ,4965.517,106.741700,106.741700,106.741700
XS GIS Cut Line= 3
1237888.72296068622443.1419592951237359.20907179622297.742653742
1236684.29587734622291.232237056
#Sta/Elev= 30
9746.393190.54579783.674180.09969810.892170.58189872.133158.2321 9912.96 153.908
9936.776153.09049994.615148.040910083.07149.585310116.32151.4653 10127.3151.3779
10137.51 149.45410239.58151.645310320.32151.379510343.28148.115710379.37 152.411
10399.06 150.58310448.27151.597810490.93149.3387 10546.7148.631710589.36150.2881
10628.73149.621810658.26151.7329 10720.6153.1814 10789.5158.256510812.46158.2307
10845.27161.309810871.52161.662910894.49165.304210940.42169.477110970.45174.1829
#Mann= 3 , 0 , 0
9746.393  0.0605       09746.393  0.0605       010970.45  0.0605       0
#XS Ineff= 2 , 0
       0                10304.36       0
Bank Sta=9746.393,10970.45
Exp/Cntr=0.3,0.1

Type RM Length L Ch R = 1 ,4858.775,247.774600,247.774600,247.774600
XS GIS Cut Line= 3
1237905.65004402622308.593348175 1237409.1222662622232.204459295
1236829.26115513622131.510014847
#Sta/Elev= 30
9754.788170.6002 9791.69163.90079874.676152.30249924.467148.48189984.217145.7363
10014.09145.482210103.72150.217910126.95147.256710133.59148.292710196.66149.4959
10256.41148.562310296.37149.750410316.35148.321810339.66148.981410372.96146.4826
10446.21147.621810479.51 145.67710502.82146.639610526.13145.793810569.42148.4443
 10589.4147.914210609.38149.700910646.01150.142310712.61154.726410769.22159.8956
 10789.2163.089810799.19166.683710812.51169.220710839.15169.5181 10845.7170.8901
#Mann= 3 , 0 , 0
9754.788   0.045       09754.788   0.045       0 10845.7   0.045       0
#XS Ineff= 2 , 0
       0                 10306.4       0
Bank Sta=9754.788,10845.7
Exp/Cntr=0.3,0.1

Type RM Length L Ch R = 1 ,4611.001,135.040400,135.040400,135.040400
XS GIS Cut Line= 2
1237968.44904092622246.1222833541236883.42782179621846.604536444
#Sta/Elev= 30
9527.762172.3089 9560.13167.6725  9588.1 164.8619658.836154.62979672.008154.6195
9703.474150.18499759.412147.39279818.847 145.0579874.786145.59269909.748147.2112
9930.725  144.939993.656 146.16610018.13144.206810102.04 143.42110119.52144.1794
10192.94142.700810255.87143.685510343.27147.944210364.25147.883110416.69152.4328
10437.67152.557710455.15154.134710497.11155.708210539.06158.065210549.55159.3881
10601.99161.514510629.96164.076810647.44163.672310664.92 166.194   10684167.5746
#Mann= 3 , 0 , 0
9527.762   0.045       09527.762   0.045       0   10684   0.045       0
#XS Ineff= 2 , 0
       0                 10213.5       0
Bank Sta=9527.762,10684
Exp/Cntr=0.3,0.1

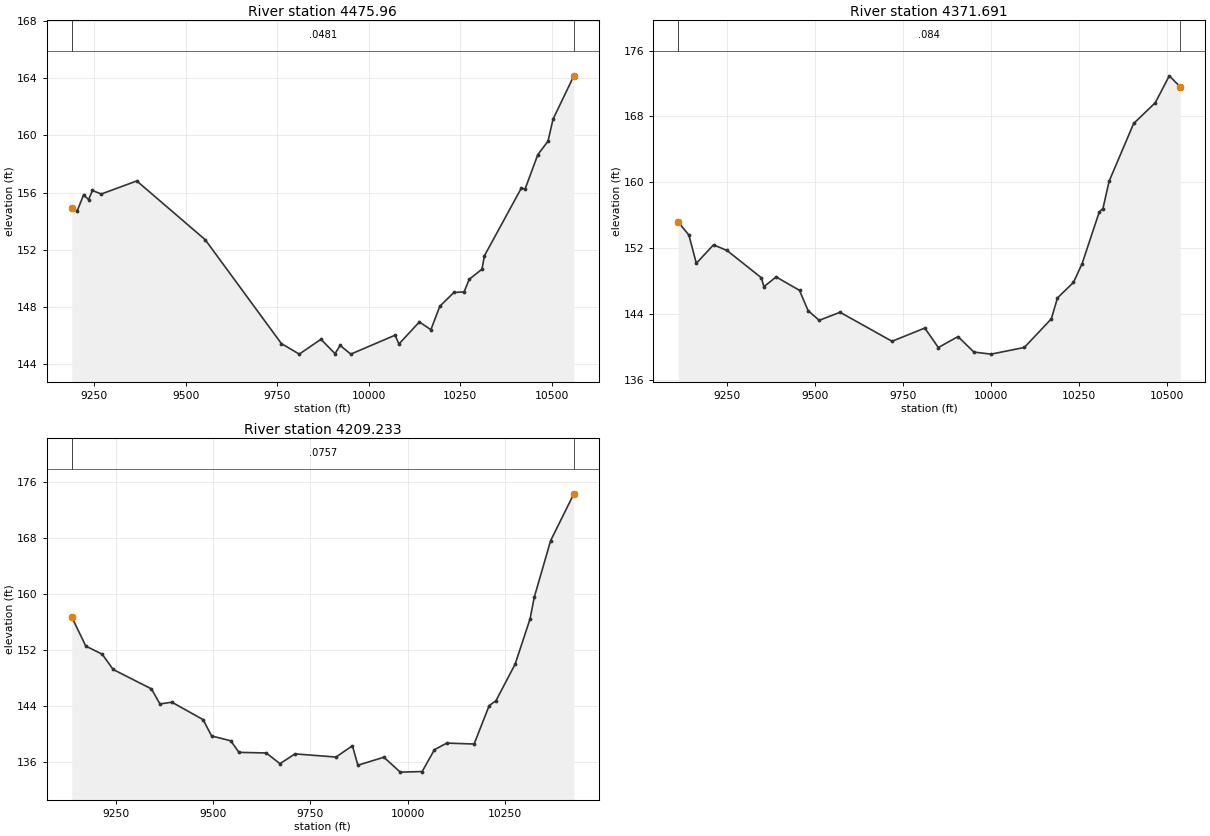
Type RM Length L Ch R = 1 , 4475.96,104.269400,104.269400,104.269400
XS GIS Cut Line= 4
1238234.31516746622246.1222833541237722.70251313622073.668579638
1237206.77851623621885.4066197871236939.47527549621793.431311131
#Sta/Elev= 30
9188.844154.91079203.712154.72369221.023155.83459234.872155.51549245.259156.1482
9269.494155.90099366.436156.81449553.395  152.719761.411 145.4549810.305144.7125
9869.676145.74719908.093144.74749922.063145.32059951.173144.711810072.24146.0355
10082.71145.420610138.59146.962910170.03146.417110194.47148.061910232.89149.0187
10260.83 149.063 10274.8149.944810309.52150.645910316.45151.592910417.07156.3108
10427.48156.254610462.18158.653910489.94159.590110503.81161.133910560.62 164.161
#Mann= 3 , 0 , 0
9188.844  0.0481       09188.844  0.0481       010560.62  0.0481       0
#XS Ineff= 2 , 0
       0                10150.86       0
Bank Sta=9188.844,10560.62
Exp/Cntr=0.3,0.1

Type RM Length L Ch R = 1 ,4371.691,162.457600,162.457600,162.457600
XS GIS Cut Line= 2
1238340.66161805622191.5119438621236999.83407176621697.144659907
#Sta/Elev= 30
9110.213155.16179140.665153.56269161.645150.1383  9210.6152.38139249.064151.6968
9346.972148.37489353.966147.29459388.933148.48129455.371146.84899479.848144.3829
9511.318143.20389570.763144.1847 9718.69140.65649812.037142.26419850.501139.8959
9906.449141.22359951.907139.340710000.86 139.09310095.27139.9047 10172.2 143.385
10189.68145.933510235.14147.814510259.62150.087210308.57156.383110319.06156.7996
10336.55160.114510406.48167.142910467.92169.662410507.89172.939310539.27171.5877
#Mann= 3 , 0 , 0
9110.213   0.084       09110.213   0.084       010539.27   0.084       0
#XS Ineff= 2 , 0
       0                               0
Bank Sta=9110.213,10539.27
Exp/Cntr=0.3,0.1

Type RM Length L Ch R = 1 ,4209.233,0.000000,0.000000,0.000000
XS GIS Cut Line= 2
 1238391.7611551622051.6489037281237186.90004402621593.315570399
#Sta/Elev= 30
9137.697156.68289173.796152.53679215.919151.3736    9244149.19019342.286146.4133
 9364.04144.26419394.939144.5062 9474.77142.01979496.734139.67929545.877138.9867
9566.938137.33339637.142137.24539672.244135.71119710.856137.1168 9816.19136.6619
9858.284138.28069872.325135.49279939.019136.63759981.141134.5052 10037.3134.5891
 10068.9137.716510100.49138.659110170.69138.5256 10209.3144.008110226.85144.7252
   10276 149.94710314.48156.444810325.14159.525410367.26167.631310426.79174.3195
#Mann= 3 , 0 , 0
9137.697  0.0757       09137.697  0.0757       010426.79  0.0757       0
#XS Ineff= 2 , 0
       0                               0
Bank Sta=9137.697,10426.79
Exp/Cntr=0.3,0.1